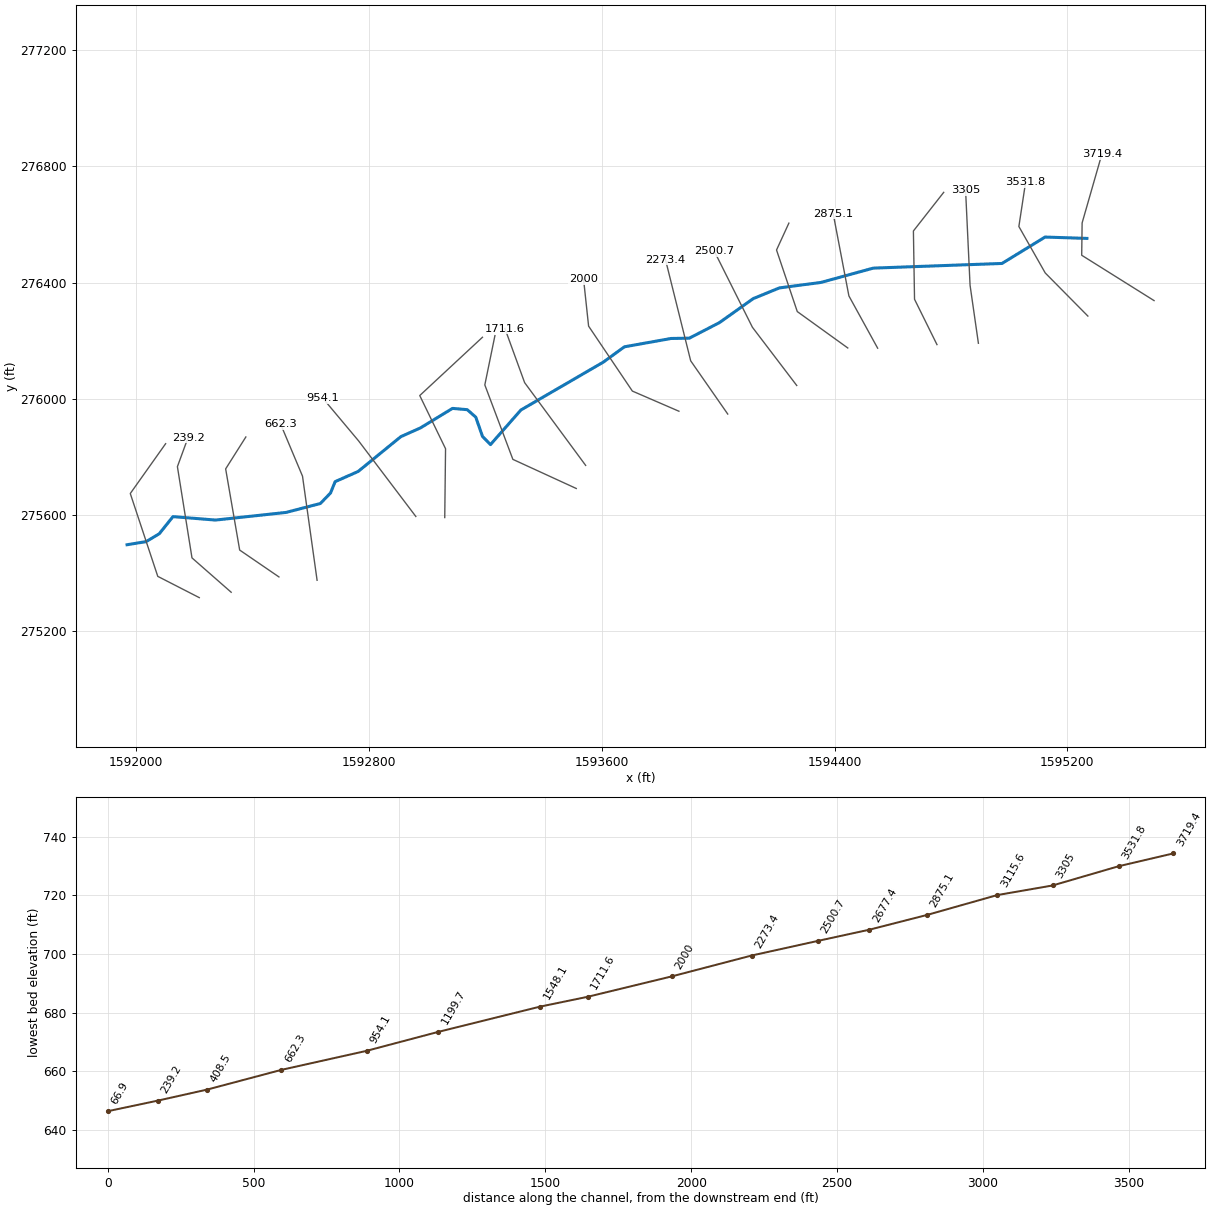
--- lftfrkmllr.prj (project) ---

Proj Title=lftfrkmllr
Current Plan=p01
Default Exp/Contr=0,0
English Units
Geom File=g01
Flow File=f01
Plan File=p01
BEGIN DESCRIPTION:
END DESCRIPTION:
DSS Export Rating Curves= 0
DSS Export Rating Curve Sorted= 0
DSS Export Volume Flow Curves= 0
DXF OffsetX= 0
DXF OffsetY= 0
DXF ScaleX= 0
DXF ScaleY= 0

--- lftfrkmllr.p01 (plan) ---

Plan Title=Approximate Study - 100yr
Program Version=4.00
Geom File=g01
Flow File=f01
Subcritical Flow
K Sum by GR= 0
Std Step Tol= 0.01
Critical Tol= 0.01
Num of Std Step Trials= 20
Max Error Tol= 0.3
Flow Tol Ratio= 0.001
Split Flow NTrial= 30
Split Flow Tol= 0.02
Split Flow Ratio= 0.02
Log Output Level= 0
Friction Slope Method= 1
Unsteady Friction Slope Method= 2
Unsteady Bridges Friction Slope Method= 1
Parabolic Critical Depth
Global Vel Dist= 0 , 0 , 0
Global Log Level= 0
CheckData=True
Encroach Param=-1 ,0,0, 0
Run HTab= 0
Run UNet= 0
Run PostProcess= 0
Run WQNet= 0
UNET Theta= 0
UNET Theta Warmup= 0
UNET ZTol= 0
UNET ZSATol= 0
UNET MxIter= 0
UNET MaxInSteps= 0
UNET DtIC= 0
UNET DtMin= 0
UNET MaxCRTS= 0
UNET WFStab= 0
UNET SFStab= 0
UNET WFX= 1
UNET SFX= 1
UNET DSS MLevel= 1
UNET DZMax Abort= 0
UNET Convert EG Bridges= 0
UNET Use Existing IB Tables= 0
UNET Froude Reduction=False
UNET Froude Limit= 0
UNET Froude Power= 0
UNET Time Slicing=0,0, 5
Write IC File= 0
Echo Input=False
Echo Output=False
Write Detailed= 0
Detailed Automatic Start=False, 0
WQ ULTIMATE=-1
WQ Max Comp Step=1HOUR
WQ Output Interval=15MIN
WQ Output Selected Increments= 0
WQ Output face flow=0
WQ Output face velocity=0
WQ Output face area=0
WQ Output face dispersion=0
WQ Output cell volume=0
WQ Output cell surface area=0
WQ Output cell continuity=0
WQ Output face conc=0
WQ Output face dconc_dx=0
WQ Output face courant=0
WQ Output face peclet=0
WQ Output face adv mass=0
WQ Output face disp mass=0
WQ Output cell mass=0
WQ Output cell source sink temp=0
WQ Output cell source sink nsm=0
WQ Output MaxMinRange=-1
WQ Daily Max Min Mean=-1
WQ Daily Range=0
WQ Daily Time=0
WQ Create Restart=0
WQ Fixed Restart=0
WQ System Summary=False
Sorting and Armoring Iterations= 10
XS Update Threshold= 0.02
Hydraulics Update Threshold= 0.02
Energy Slope Method= 1
Volume Change Method= 0
XS Weighting Method= 0
Number of US Weighted Cross Sections= 1
Number of DS Weighted Cross Sections= 1
Upstream XS Weight=0.25
Main XS Weight=0.5
Downstream XS Weight=0.25
Number of DS XS's Weighted with US Boundary= 1
Upstream Boundary Weight= 1
Weight of XSs Associated with US Boundary= 0
Number of US XS's Weighted with DS Boundary= 1
Downstream Boundary Weight= 0.5
Weight of XSs Associated with DS Boundary= 0.5
Sediment Output Level= 4
Mass or Volume Output= 0
Output Increment Type= 1
Profile and TS Output Increment= 10
XS Output Flag= 0
XS Output Increment= 10
Disregard all LS=0
Disregard all Conn=0
Disregard all Breaches=0
Disregard all Pumps=0

--- lftfrkmllr.f01 (steady flow) ---

Flow Title=USGS Regression Equation
Program Version=4.00
Number of Profiles= 1
Profile Names=P100yr
River Rch & RM=lftfrkmllr,Main            ,3719.4
     366
River Rch & RM=lftfrkmllr,Main            ,3115.6
     371
River Rch & RM=lftfrkmllr,Main            ,2273.4
     407
River Rch & RM=lftfrkmllr,Main            ,239.2
     445
Boundary for River Rch & Prof#=lftfrkmllr,Main            , 1
Up Type= 0
Dn Type= 3
Dn Slope=0.023258
DSS Import GetInterval= 0
DSS Import GetPeak= 0
DSS Import FillOption= 0

--- lftfrkmllr.g01 (geometry) ---

Geom Title=USGS 3m DEM
Program Version=4.00

River Reach=lftfrkmllr      ,Main
Reach XY= 30
     1595267.028      276551.897     1595123.326      276556.585
     1594975.189      276465.674     1594532.999      276449.621
     1594353.157      276400.302     1594210.467      276381.482
     1594120.587       276344.64     1594004.309      276261.897
     1593900.799      276208.339     1593838.256      276207.382
     1593677.896      276178.674     1593605.614      276126.024
     1593322.148      275960.996     1593217.825      275841.976
     1593190.426      275870.132     1593167.252      275936.603
     1593137.981      275962.215     1593087.391       275966.68
     1592977.044      275899.365      1592909.73      275869.296
     1592763.213       275749.56     1592684.048      275714.408
     1592668.329      275675.435     1592633.308      275639.176
     1592515.474      275608.474     1592273.271      275582.204
      1592126.95      275594.027      1592079.73      275534.924
     1592034.804      275507.962     1591969.068      275497.221

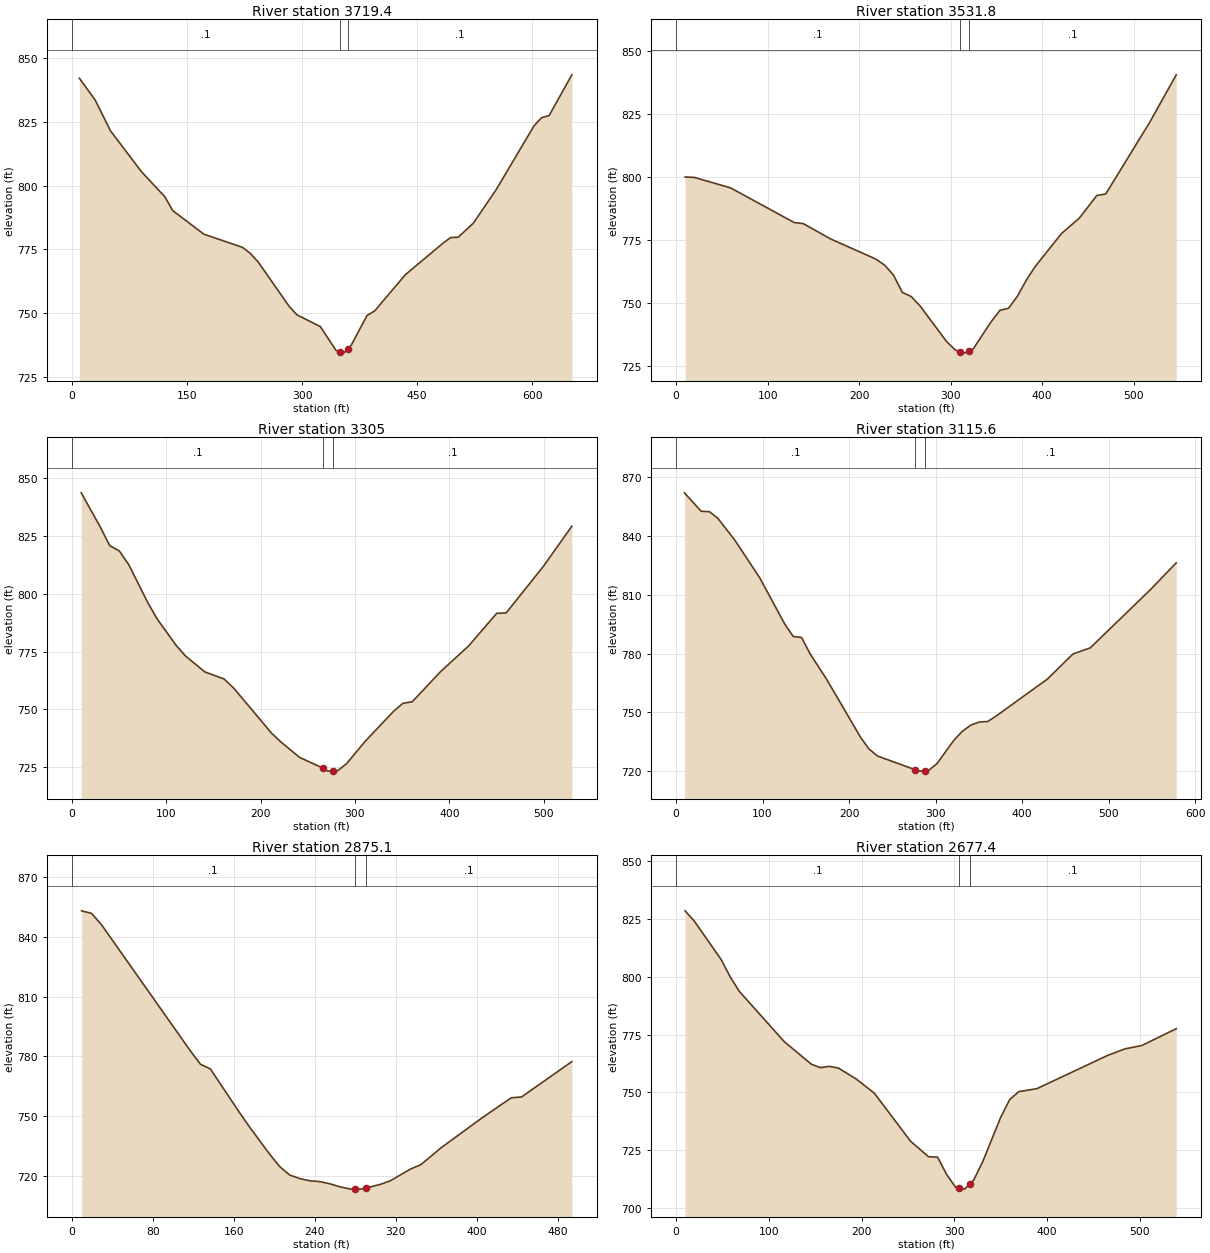
Type RM Length L Ch R = 1 ,3719.4  ,176.3,187.6,198.9
XS GIS Cut Line= 4
     1595497.696        276337.8     1595249.069      276493.915
     1595250.514      276605.219     1595318.453      276842.283
#Sta/Elev= 30
    10.1  842.04    30.4  833.61    50.6  821.43    91.1  805.36   121.5  795.56
   131.6  790.19   172.1  780.97   222.7  775.75   232.8  773.39     243  770.03
   283.5  752.57   293.6  749.31   323.9  744.73   344.2  735.45   349.3  734.88
   354.3  734.33   359.3  735.94   364.4  737.58   384.7  749.08   394.8  750.91
   434.5  765.03   483.8  777.45   493.7  779.63   503.5  779.75   523.3  785.29
   552.9  798.39   602.2  823.38     612  826.57   621.9  827.45   651.5  843.39
#Mann= 3 , 0 , 0
       0      .1       0   349.3    .045       0   359.3      .1       0
Bank Sta=349.3,359.3
XS Rating Curve= 0 ,0
Exp/Cntr=0.3,0.1

Type RM Length L Ch R = 1 ,3531.8  ,237.3,226.8,216.4
XS GIS Cut Line= 4
     1595270.269      276284.557     1595123.791      276432.963
     1595033.206      276592.932     1595056.334      276745.193
#Sta/Elev= 30
     9.9  799.84    19.9  799.69    59.6  795.52   129.1  781.76     139  781.35
   168.8  775.27   218.2  767.29   227.9  764.86   237.5  760.93   247.2  754.05
   256.9  752.41   266.6  748.68   295.6  734.52   305.3  731.11   309.8  730.57
     315  729.96   320.1  730.84   324.6  731.63     344  742.32   353.7  746.91
   363.3  747.79     373  752.58   382.7  758.98   392.4  764.36   421.2  777.46
   440.5  783.52   459.7  792.53   469.4   793.1   517.5  821.58   546.4  840.38
#Mann= 3 , 0 , 0
       0      .1       0   309.8    .045       0   320.1      .1       0
Bank Sta=309.8,320.1
XS Rating Curve= 0 ,0
Exp/Cntr=0.3,0.1

Type RM Length L Ch R = 1 ,3305    ,190.1,189.4,188.7
XS GIS Cut Line= 3
      1594894.18      276190.898     1594865.527      276390.561
     1594850.108       276718.21
#Sta/Elev= 30
    10.1  843.56    30.3  828.81    40.3  820.74    50.4   818.5    60.5  812.52
    80.7  796.06    90.8  788.95   110.9  777.54     121  772.93   141.2  766.19
   161.4  763.17   171.5  759.29   211.6  739.82   221.6  735.97   241.5  729.27
     266  724.71   271.3  723.38   276.6  723.39   281.2   723.4   291.2  726.64
     311  736.34   340.9  749.21   350.8  752.67   360.7  753.35   390.6  766.32
   420.4  777.46   450.2  791.55   460.1  791.67   499.9     812   529.7  829.16
#Mann= 3 , 0 , 0
       0      .1       0     266    .045       0   276.6      .1       0
Bank Sta=266,276.6
XS Rating Curve= 0 ,0
Exp/Cntr=0.3,0.1

Type RM Length L Ch R = 1 ,3115.6  ,236.8,240.5,244.1
XS GIS Cut Line= 4
     1594751.813      276186.262      1594674.72      276342.377
     1594670.865      276577.514     1594774.942        276710.5
#Sta/Elev= 30
     9.7   861.9      29  852.51    38.7  852.29    48.4  848.88    67.7  837.95
    96.7  818.63   125.7  795.01   135.4  788.74   145.1  788.21   154.8     780
   174.1  766.88   213.3  737.33   223.1  731.37   232.9   727.8   276.5  720.83
   281.9  720.11   287.3  720.27   291.7   720.4   301.5  723.88   321.1  735.79
   330.9  740.39   340.7  743.54   350.5  745.12   360.3  745.39   370.1   748.2
   429.1  766.96   458.9  779.82   478.8  782.91   548.4  812.58   578.2  826.23
#Mann= 3 , 0 , 0
       0      .1       0   276.5    .045       0   287.3      .1       0
Bank Sta=276.5,287.3
XS Rating Curve= 0 ,0
Exp/Cntr=0.3,0.1

Type RM Length L Ch R = 1 ,2875.1  ,194.7,197.6,200.6
XS GIS Cut Line= 3
     1594548.008      276173.968      1594449.22      276353.942
     1594395.255      276637.261
#Sta/Elev= 30
     9.8   853.2    19.6  851.92    29.3  846.32   117.3  782.72   127.1  776.11
   136.9  773.74   166.2  751.41     176  744.27   195.5  730.83   205.3  724.69
   215.2  720.41   225.2  718.62   235.1   717.5   245.1   717.1     255     716
     265  714.45   274.9  713.39   279.3  713.37   284.9  713.33   290.4  713.86
   304.8  715.74   314.7  717.57   334.6  723.48   344.5  725.56   364.4  734.02
   404.2  748.83   424.1  755.84     434  759.25     444  759.63   493.7  777.43
#Mann= 3 , 0 , 0
       0      .1       0   279.3    .045       0   290.4      .1       0
Bank Sta=279.3,290.4
XS Rating Curve= 0 ,0
Exp/Cntr=0.3,0.1

Type RM Length L Ch R = 1 ,2677.4  ,173.8,176.7,179.7
XS GIS Cut Line= 4
     1594445.366      276174.698     1594271.905      276299.976
     1594200.593      276511.984     1594242.994      276604.496
#Sta/Elev= 30
     9.7  828.36    19.5  824.03    48.6  807.36    58.4  799.88    68.1  793.67
   116.7  771.92   145.9  762.19   155.6   760.7   165.3  761.27   175.1  760.52
   194.5  755.76     214  749.61   252.9  728.96   272.3  722.25     282   722.1
   291.8  714.65   301.5  709.08   305.5  708.75   311.2   708.3   316.9  710.58
   320.9  712.18   330.7  720.12   350.1  739.29   359.8  746.93   369.6  750.36
     389  751.62   465.4  765.98   483.9  768.78   502.4  770.28   539.4  777.51
#Mann= 3 , 0 , 0
       0      .1       0   305.5    .045       0   316.9      .1       0
Bank Sta=305.5,316.9
XS Rating Curve= 0 ,0
Exp/Cntr=0.3,0.1

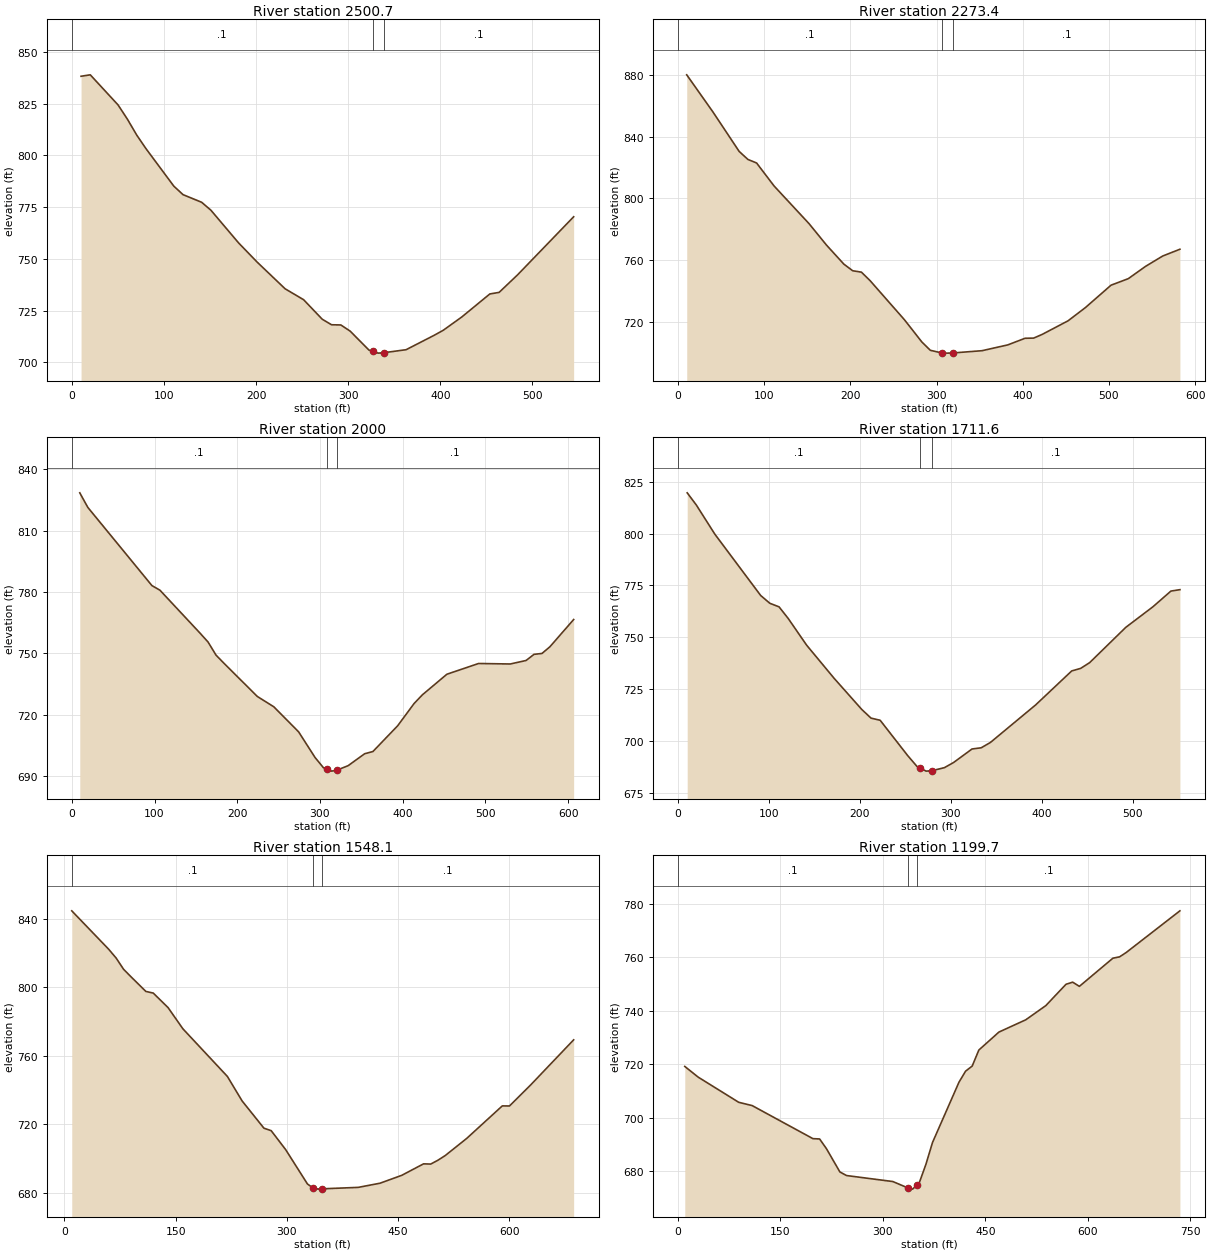
Type RM Length L Ch R = 1 ,2500.7  ,232,227.3,222.6
XS GIS Cut Line= 3
     1594269.977      276045.566     1594117.717       276246.01
     1593986.657      276508.129
#Sta/Elev= 30
    10.1  838.18    20.1  838.87    50.3  824.31    60.4  817.46    70.5  809.79
    80.5  803.26   110.8  785.11   120.8     781     141  777.32     151  773.51
   181.2  757.65   201.4  748.36   231.6  735.54   251.7  730.26   271.9  720.84
     282  718.17   292.1  718.07   302.2   715.1   322.5  705.99   326.7  705.36
   332.6  704.47   338.4  704.65   362.9  706.12   393.2  713.03   403.3  715.52
   423.5  721.97   453.8  733.04   463.9   733.8   484.1  742.35   544.8  770.32
#Mann= 3 , 0 , 0
       0      .1       0   326.7    .045       0   338.4      .1       0
Bank Sta=326.7,338.4
XS Rating Curve= 0 ,0
Exp/Cntr=0.3,0.1

Type RM Length L Ch R = 1 ,2273.4  ,265.9,273.4,280.8
XS GIS Cut Line= 3
     1594032.914      275947.272     1593905.709      276130.369
     1593818.978      276479.219
#Sta/Elev= 30
    10.1  880.17    40.5  856.08    70.9  830.48    81.1  825.23    91.2  822.92
   111.5  807.98     152  783.56   172.3  769.62   192.5  757.22   202.7  752.96
   212.8  752.05   222.9  746.52   262.9  721.04   282.9  706.74   292.8   701.3
   306.8   699.5   312.8  699.47   318.8  699.57   352.8  701.05   382.7  704.82
   402.7  709.11   412.7  709.23   422.7  711.66   452.6  720.45   472.6  728.98
   502.5  743.59   522.5  747.82   542.5  755.79   562.4  762.51   582.4  766.93
#Mann= 3 , 0 , 0
       0      .1       0   306.8    .045       0   318.8      .1       0
Bank Sta=306.8,318.8
XS Rating Curve= 0 ,0
Exp/Cntr=0.3,0.1

Type RM Length L Ch R = 1 ,2000    ,287.5,288.4,289.3
XS GIS Cut Line= 4
     1593865.235      275956.908     1593705.265      276026.293
     1593554.932      276249.865     1593537.586      276411.762
#Sta/Elev= 30
     9.7  828.47    19.4  821.35    96.9   783.1   106.6  780.84     155  759.87
   164.7  755.52   174.4  749.08   184.3  744.98   224.3  728.87   244.2  723.83
   274.2  711.57   294.1     699   304.1  694.08   307.9  693.43   314.1  692.36
   320.2  692.79     334  695.02     354  700.86     364  701.95   393.9  714.54
   413.8  725.45   423.8  729.69   453.4  739.75   491.7     745     530  744.76
   549.1  746.47   558.7  749.48   568.3   749.9   577.9  753.18   606.6   766.5
#Mann= 3 , 0 , 0
       0      .1       0   307.9    .045       0   320.2      .1       0
Bank Sta=307.9,320.2
XS Rating Curve= 0 ,0
Exp/Cntr=0.3,0.1

Type RM Length L Ch R = 1 ,1711.6  ,170.6,163.4,157.2
XS GIS Cut Line= 3
     1593544.797      275770.408     1593335.215      276055.203
     1593267.469      276241.567
#Sta/Elev= 30
    10.1  819.62    20.2   813.7    40.4  799.74    90.9   770.1     101  766.34
   111.1  764.62   121.2     759   141.4  746.16   171.7  730.13   202.1  715.12
   212.2  710.96   222.3  709.91   252.6  692.86   262.7  687.69   266.4  686.85
   272.8  685.39   279.1  685.58     293  687.07   303.1  689.57   323.3  696.07
   333.4  696.65   343.5  699.21   393.3  717.34   432.9  733.71   442.8  734.95
   452.7  737.74   492.4  754.74   522.2  764.65     542  772.23   551.9  772.91
#Mann= 3 , 0 , 0
       0      .1       0   266.4    .045       0   279.1      .1       0
Bank Sta=266.4,279.1
XS Rating Curve= 0 ,0
Exp/Cntr=0.3,0.1

Type RM Length L Ch R = 1 ,1548.1  ,346.6,348.5,346.4
XS GIS Cut Line= 4
      1593512.53      275690.935     1593294.741      275791.157
     1593198.373      276047.493     1593233.065        276217.1
#Sta/Elev= 30
      10   844.6    59.9  822.11    69.9  816.98    79.9  810.44    89.9  806.06
   109.9  797.52   119.9  796.55   139.9  788.05   159.8   775.7   219.8  747.88
   239.7  733.54   269.1  717.64   278.9  716.17   298.4  705.11   327.8  685.03
   335.3  682.69   337.5  682.03   347.3   682.2   396.2  683.05   425.6  685.48
   454.9  690.08   484.3  696.79     494  696.67   503.8  698.93   513.6  701.66
   542.4  711.61   590.5  730.65   600.2   730.6     629  743.01   686.7  769.24
#Mann= 3 , 0 , 0
      10      .1       0   335.3    .045       0   347.3      .1       0
Bank Sta=335.3,347.3
XS Rating Curve= 0 ,0
Exp/Cntr=0.3,0.1

Type RM Length L Ch R = 1 ,1199.7  ,241.4,245.6,249.8
XS GIS Cut Line= 4
     1593060.693      275590.823     1593063.459      275827.776
     1592974.801      276010.874      1593190.25      276211.552
#Sta/Elev= 30
     9.9  719.21    29.6   715.2    88.9  705.82   108.6  704.59   197.5  692.26
   207.3  692.14   217.2  688.56     237  679.83   246.7  678.49   314.5  676.25
   336.8  673.85   343.5  673.42   350.2  675.05   353.2  675.79   362.9  682.65
   372.6  690.83   411.3   713.3     421  717.44   430.7  719.35   440.4  725.32
   469.8  732.03   509.1  736.61   538.5  741.91     568  749.86   577.8  750.66
   587.6  749.09   636.7   759.6   646.5  760.11   656.3  761.75   734.8  777.28
#Mann= 3 , 0 , 0
       0      .1       0   336.8    .045       0   350.2      .1       0
Bank Sta=336.8,350.2
XS Rating Curve= 0 ,0
Exp/Cntr=0.3,0.1

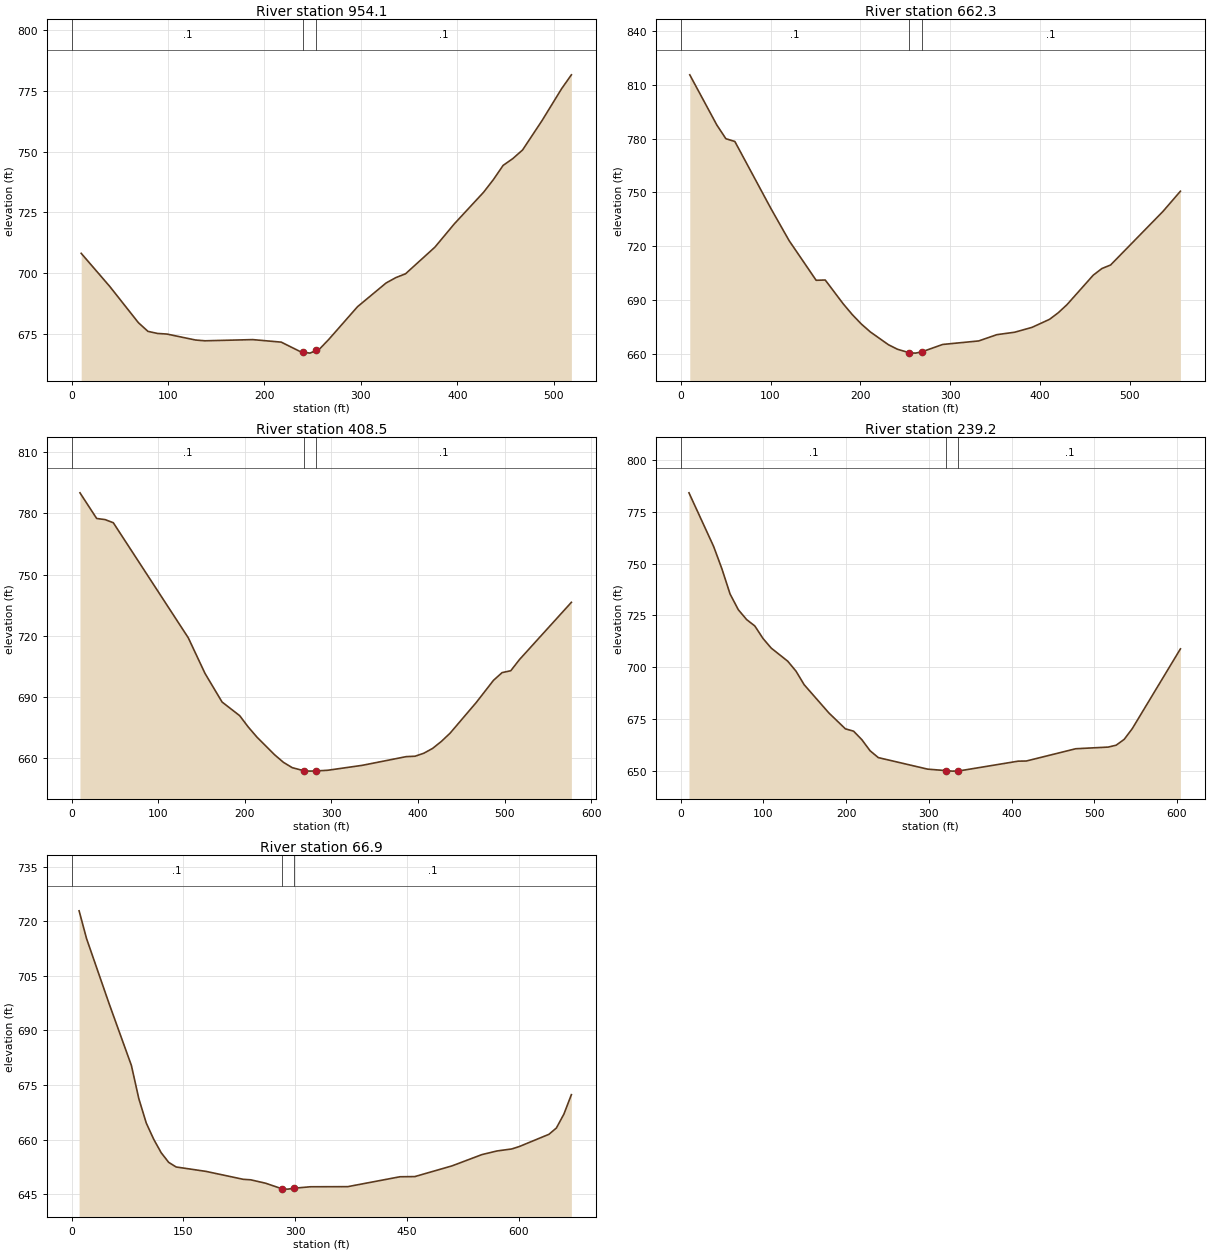
Type RM Length L Ch R = 1 ,954.1   ,302.3,291.8,281.3
XS GIS Cut Line= 3
      1592961.31      275594.567     1592764.721      275854.759
     1592641.434      276002.188
#Sta/Elev= 30
     9.9  708.08    39.5  694.45    69.2  679.51    79.1  675.93    88.9  675.07
    98.8  674.81   128.5  672.35   138.3  672.03   187.8  672.52   217.4  671.48
   237.2  667.56   240.2  667.38   247.1  666.95   253.9  668.06   256.9  668.55
   266.8  672.65   296.5  686.09   326.1  695.85   336.2  698.07   346.3  699.65
   376.7   710.6   396.9  720.23   427.3  733.28   437.4  738.46   447.5  744.32
   457.6  747.13   467.7  750.69   487.9  762.81   508.2  775.95   518.3  781.65
#Mann= 3 , 0 , 0
       0      .1       0   240.2    .045       0   253.9      .1       0
Bank Sta=240.2,253.9
XS Rating Curve= 0 ,0
Exp/Cntr=0.3,0.1

Type RM Length L Ch R = 1 ,662.3   ,253.1,253.8,254.5
XS GIS Cut Line= 3
     1592622.097       275374.85     1592571.986      275733.336
      1592496.82      275912.579
#Sta/Elev= 30
    10.1  815.59    40.2  787.64    50.3  779.98    60.3  778.42   100.5  741.01
   120.7  723.16   150.8  701.05   160.9  701.22     181  687.88     191  681.95
   201.1  676.68   211.2  672.24   231.3  665.13   241.3  662.62   254.4  660.68
   261.4  660.46   268.5  661.18   291.6  665.29   331.8  667.26   351.9  670.75
   371.7   672.1   391.1  674.82   410.6   679.3   420.3  682.97     430  687.46
   459.2   703.9   468.9  707.62   478.6   709.6   536.9  739.47   556.3  750.72
#Mann= 3 , 0 , 0
       0      .1       0   254.4    .045       0   268.5      .1       0
Bank Sta=254.4,268.5
XS Rating Curve= 0 ,0
Exp/Cntr=0.3,0.1

Type RM Length L Ch R = 1 ,408.5   ,168.9,169.2,169.6
XS GIS Cut Line= 4
     1592491.038      275386.414     1592356.123      275478.927
      1592307.94      275758.392     1592377.324       275868.25
#Sta/Elev= 30
     9.6  790.01    28.9  777.45    38.5  776.91    48.1  775.37   134.7  719.02
     154   701.6   173.7  687.59     194  680.92   204.1  675.27   214.2   670.3
   234.5  661.71   244.6  658.05   254.7  655.45   267.8  653.98     275  653.75
   282.2  653.86   295.3  654.15   335.8   656.6   386.4  660.85   396.5  661.04
   406.7  662.51   416.8  664.86   426.9  668.27     437  672.32   467.2  687.34
   487.2  698.23   497.1  701.99   507.1   702.9   517.1  708.34   577.1   736.4
#Mann= 3 , 0 , 0
       0      .1       0   267.8    .045       0   282.2      .1       0
Bank Sta=267.8,282.2
XS Rating Curve= 0 ,0
Exp/Cntr=0.3,0.1

Type RM Length L Ch R = 1 ,239.2   ,169.2,172.3,175.4
XS GIS Cut Line= 4
     1592326.932      275333.649     1592192.299      275451.944
     1592142.188      275766.101     1592178.808      275866.323
#Sta/Elev= 30
      10  784.05    39.8  758.23    49.8  747.47    59.7   735.3    69.7  727.71
    79.7  722.99    89.6  719.91    99.6  713.83   109.5  709.22   129.4  702.94
   139.4  698.13   149.3  691.59   179.2  677.98   199.1  670.35     209  669.23
     219  665.12   228.9  659.81   238.9  656.49   298.5  650.94     321  650.22
   328.3  649.98   335.7  650.03   407.9  654.78   417.8  654.85   477.5  660.76
   516.7  661.56   526.4  662.47   536.1  665.28   545.8   670.4   604.1  708.88
#Mann= 3 , 0 , 0
       0      .1       0     321    .045       0   335.7      .1       0
Bank Sta=321,335.7
XS Rating Curve= 0 ,0
Exp/Cntr=0.3,0.1

Type RM Length L Ch R = 1 ,66.9    ,70.3,66.9,63.5
XS GIS Cut Line= 4
     1592217.355      275315.102     1592074.731      275388.342
     1591980.291      275673.588     1592101.714      275845.122
#Sta/Elev= 30
      10   722.9      20  715.27    50.1  697.48    80.2  680.38    90.2  671.23
   100.2  664.52   110.2  660.06   120.2  656.37   130.3  653.71   140.3  652.44
   180.4  651.23   230.4  649.05   240.5  648.91   260.5  647.97   283.1  646.39
   290.5  646.35     298  646.59   320.6     647   370.7  647.03   440.8  649.75
   460.8   649.8   510.8  652.75   550.9  655.85   570.9  656.84   590.9   657.4
   600.9  658.05   640.9  661.43   650.9  663.17     661  667.01     671  672.33
#Mann= 3 , 0 , 0
       0      .1       0   283.1    .045       0     298      .1       0
Bank Sta=283.1,298
XS Rating Curve= 0 ,0
Exp/Cntr=0.3,0.1

Chan Stop Cuts=-1
Use User Specified Reach Order=0